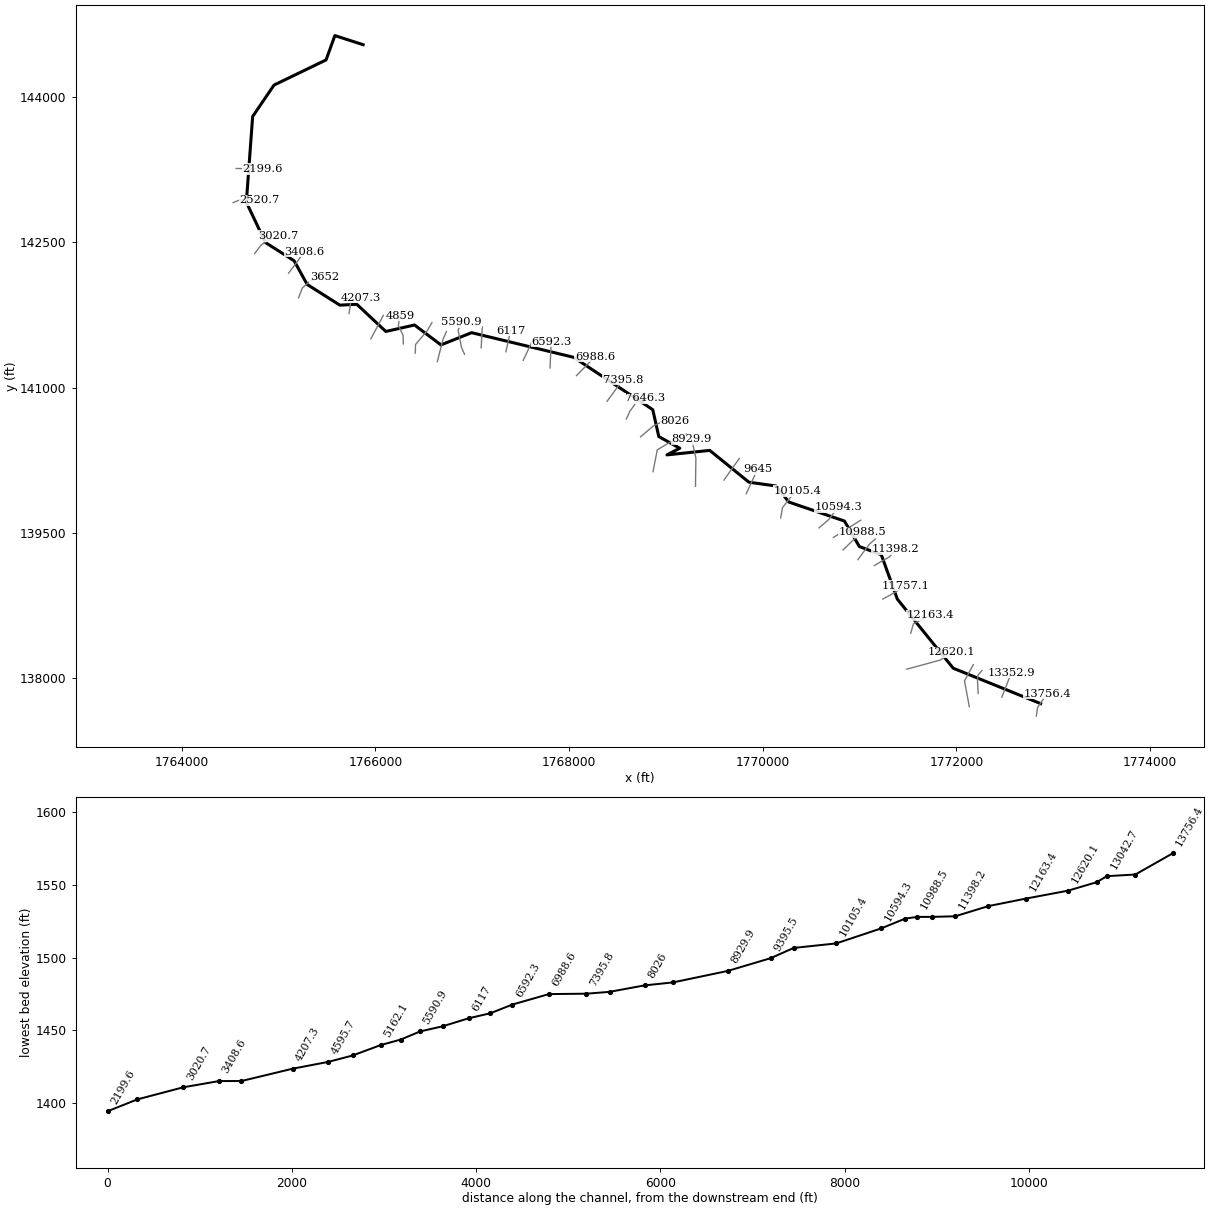
--- Big Branch B.prj (project) ---

Proj Title=Big Branch B
Current Plan=p01
Default Exp/Contr=0,0
English Units
Geom File=g01
Flow File=f01
Plan File=p01
BEGIN DESCRIPTION:
END DESCRIPTION:
DSS Export Rating Curves= 0
DSS Export Rating Curve Sorted= 0
DSS Export Volume Flow Curves= 0
DXF OffsetX= 0
DXF OffsetY= 0
DXF ScaleX= 0
DXF ScaleY= 0

--- Big Branch B.p01 (plan) ---

Plan Title=Floodplain
Program Version=4.00
Geom File=g01
Flow File=f01
K Sum by GR=0
Std Step Tol=0.01
Critical Tol=0.01
Num of Std Step Trials=20
Max Error Tol=0.3
Flow Tol Ratio=0.001
Split Flow NTrial=30
Split Flow Tol=0.02
Split Flow Ratio=0.02
Log Output Level=0
Friction Slope Method=1
Unsteady Friction Slope Method=2
Unsteady Bridges Friction Slope Method=1
Global Log Level=0
CheckData=False
Run HTab=0
Run UNet=0
Run PostProcess=0
UNET Theta=0
UNET Theta Warmup=0
UNET ZTol=0
UNET ZSATol=0
UNET MxIter=0
UNET MaxInSteps=0
UNET DtIC=0
UNET DtMin=0
UNET MaxCRTS=0
UNET WFStab=0
UNET SFStab=0
UNET WFX=0
UNET SFX=0
UNET DSS MLevel=0
UNET DZMax Abort=0
UNET Convert EG Bridges=0
UNET Use Existing IB Tables=0
UNET Froude Limit=0
UNET Froude Power=0
Write IC File=0
Echo Input=False
Echo Output=False
Write Detailed=0

--- Big Branch B.f01 (steady flow) ---

Flow Title=NFF Regression Equation
Program Version=4.00
Number of Profiles=1
Profile Names=P100yr
River Rch & RM=Big Branch B,Main      ,13756.4
578.6841
River Rch & RM=Big Branch B,Main      ,12620.1
591.3688
River Rch & RM=Big Branch B,Main      ,12620.1
838.8599
River Rch & RM=Big Branch B,Main      ,11398.2
860.8027
River Rch & RM=Big Branch B,Main      ,8337.1
948.8402
River Rch & RM=Big Branch B,Main      ,8337.1
1067.726
River Rch & RM=Big Branch B,Main      ,6592.3
1118.262
River Rch & RM=Big Branch B,Main      ,4859
1232.286
River Rch & RM=Big Branch B,Main      ,226.5
1341.757
Boundary for River Rch & Prof#=Big Branch B,Main      ,1
Up Type=0
Dn Type=3
Dn Slope=0.025277

--- Big Branch B.g01 (geometry) ---

Geom Title=Geometry
Program Version=4.00

River Reach=Big Branch B    ,Main
Reach XY= 30
     1772868.711       137737.05     1771966.363      138102.367
     1771389.335      138815.549     1771223.693      139274.033
     1770996.967       139359.02     1770842.788       139622.09
     1770268.284      139818.483     1770140.002      139983.569
     1769856.627      140023.264     1769452.001      140351.666
     1769009.951      140305.134     1769142.899      140374.101
     1768926.029      140494.584     1768863.873      140771.969
     1768047.151      141312.751     1766993.489      141567.127
     1766676.729      141441.002     1766403.788      141646.306
     1766107.549      141579.765     1765807.754      141860.214
     1765633.094      141851.476     1765295.459      142064.864
     1765160.569      142309.605     1764864.382      142497.836
     1764667.314      142914.039     1764732.377      143799.151
     1764953.182      144123.912     1765490.389      144383.386
       1765581.4      144634.829     1765873.344      144540.697

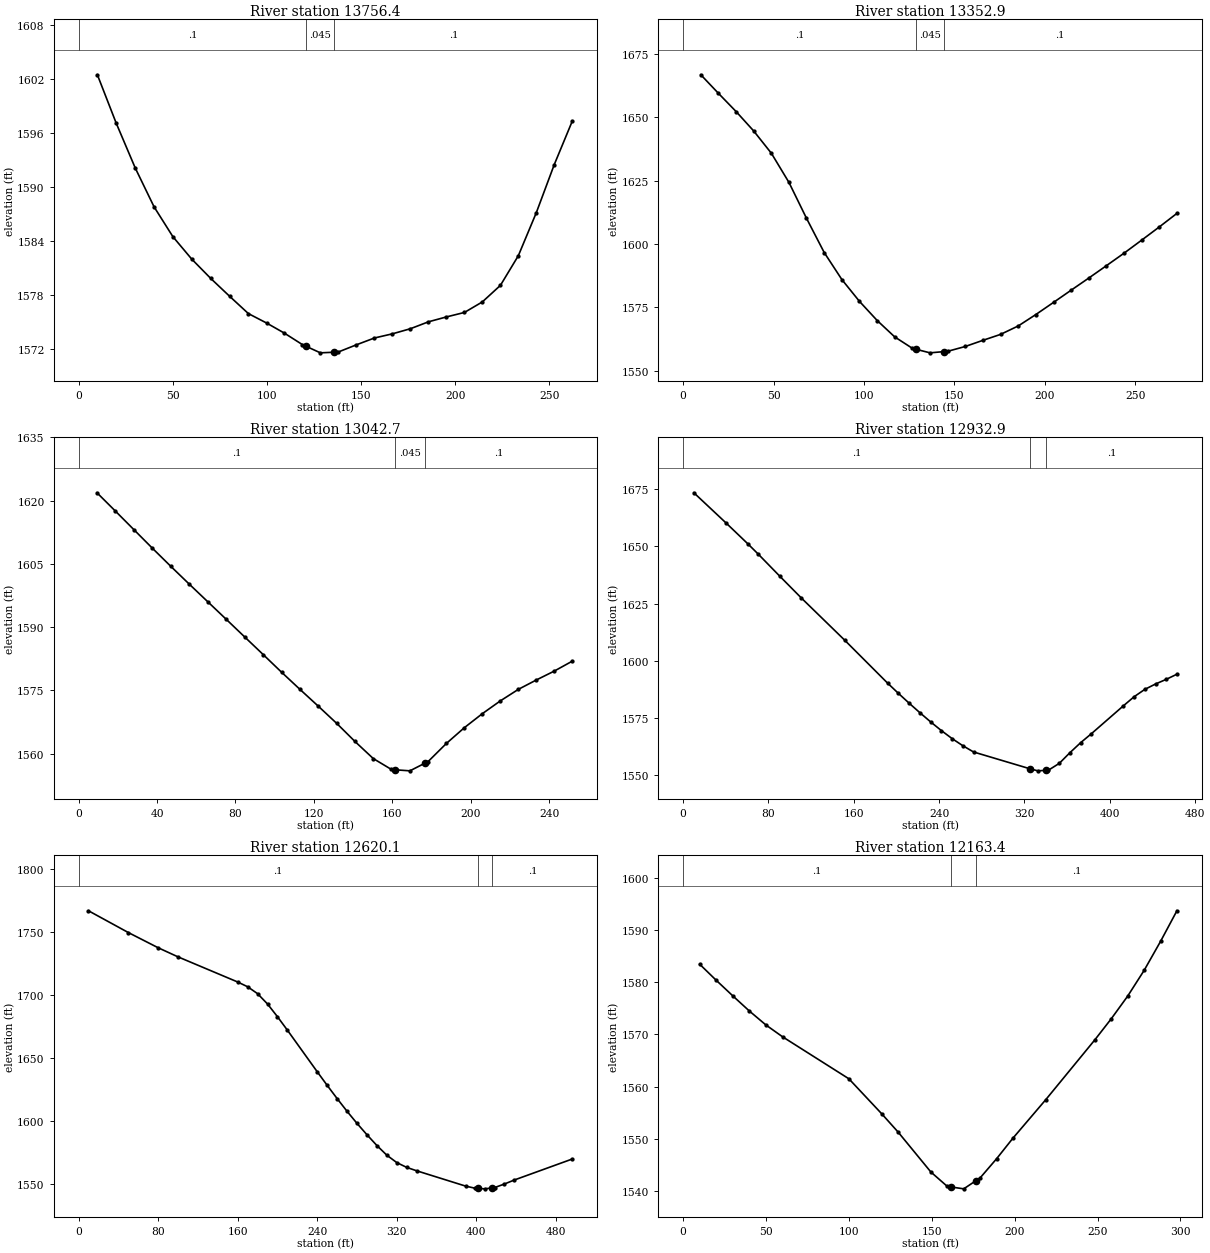
Type RM Length L Ch R = 1 ,13756.4 ,398.1,403.4,409.1
XS GIS Cut Line= 3
     1772824.651      137607.766     1772836.529      137697.195
     1772934.973      137838.198
#Sta/Elev= 29
      10 1602.47      20 1597.09    30.1 1592.11    40.1 1587.79    50.1 1584.47
    60.1 1581.98    70.2 1579.83    80.2 1577.85    90.2 1575.92    99.8 1574.88
   109.3 1573.75   118.9 1572.47   120.9 1572.28   128.4 1571.56   135.9 1571.63
     138 1571.66   147.5 1572.45   157.1 1573.21   166.6 1573.67   176.2 1574.24
   185.8 1575.01   195.3 1575.55   204.9 1576.05   214.4 1577.22     224 1579.06
   233.5 1582.35   243.1 1587.16   252.6 1592.49   262.2 1597.34
#Mann= 3 , 0 , 0
       0      .1       0   120.9    .045       0   135.9      .1       0
Bank Sta=120.9,135.9
XS Rating Curve= 0 ,0
Exp/Cntr=0.3,0.1

Type RM Length L Ch R = 1 ,13352.9 ,303.2,310.2,317.2
XS GIS Cut Line= 3
     1772468.075      137803.636     1772517.815      137930.751
     1772567.556      138057.866
#Sta/Elev= 30
     9.8 1666.78    19.5 1659.48    29.3 1652.27      39 1644.63    48.8 1635.81
    58.5 1624.33    68.2 1610.18      78 1596.65    87.8 1585.95    97.5 1577.37
   107.3 1569.81     117 1563.34   126.8 1558.82     129 1558.42   136.5 1557.06
     144 1557.53   146.3 1557.67     156 1559.57   165.8 1562.01   175.5 1564.34
   185.3 1567.68     195 1572.17   204.8 1576.97   214.5 1581.77   224.3 1586.58
     234 1591.44   243.8  1596.4   253.5 1601.52   263.3 1606.76     273 1612.09
#Mann= 3 , 0 , 0
       0      .1       0     129    .045       0     144      .1       0
Bank Sta=129,144
XS Rating Curve= 0 ,0
Exp/Cntr=0.3,0.1

Type RM Length L Ch R = 1 ,13042.7 ,119.8,109.9,99.9
XS GIS Cut Line= 4
     1772223.987      137841.863     1772216.866      137963.926
     1772220.935      138029.026      1772262.64      138077.852
#Sta/Elev= 29
     9.4 1621.85    18.8  1617.5    28.2 1613.11    37.6 1608.72      47 1604.42
    56.4  1600.2    65.8 1596.04    75.2 1591.88    84.6  1587.7    94.1 1583.49
   103.5 1579.29   112.9 1575.21   122.3  1571.2   131.6 1567.16   140.9 1562.87
   150.2 1558.83   159.5 1556.23   161.4 1556.16   168.9 1555.91   176.4 1557.69
   178.2 1558.12   187.5 1562.41   196.7 1566.16   205.8 1569.46     215  1572.5
   224.2 1575.24   233.4 1577.47   242.5 1579.57   251.7 1581.93
#Mann= 3 , 0 , 0
       0      .1       0   161.4    .045       0   176.4      .1       0
Bank Sta=161.4,176.4
XS Rating Curve= 0 ,0
Exp/Cntr=0.3,0.1

Type RM Length L Ch R = 1 ,12932.9 ,323.4,312.8,302.1
XS GIS Cut Line= 3
     1772132.409      137704.785     1772082.538      137972.511
      1772174.19      138139.611
#Sta/Elev= 30
    10.1 1673.47    40.3 1660.24    60.5 1651.21    70.6 1646.54    90.8 1636.87
   110.9 1627.39   151.3 1609.03   191.6  1590.2   201.7 1585.73   211.8 1581.41
   221.9 1577.23     232  1573.2   242.1 1569.38   252.2 1565.86   262.2 1562.76
   272.3 1560.01     325 1552.68   332.5 1551.76     340 1551.98   342.5 1552.06
   352.6 1555.02   362.6  1559.7   372.6 1564.06   382.7    1568   412.8 1580.25
   422.8  1584.2   432.8 1587.42   442.9 1589.78   452.9 1591.81   462.9 1594.06
#Mann= 3 , 0 , 0
       0      .1       0     325    .045       0     340      .1       0
Bank Sta=325,340
XS Rating Curve= 0 ,0
Exp/Cntr=0.3,0.1

Type RM Length L Ch R = 1 ,12620.1 ,460.3,456.7,453.2
XS GIS Cut Line= 3
     1771487.433       138092.77     1771834.772      138187.349
     1771945.401      138267.308
#Sta/Elev= 30
      10 1766.53      50 1749.28      80 1737.21     100 1729.97     160 1710.03
     170 1706.25     180 1700.77     190 1692.59     200 1682.48     210  1671.8
     240  1638.8     250 1628.02     260 1617.53     270 1607.42     280 1597.84
     290 1588.82     300 1580.27     310 1572.59     320 1566.73     330 1562.92
     340 1560.23   389.2 1548.09     399 1546.35   401.2 1546.25   408.7 1545.92
   416.2 1546.73   418.5 1546.98   428.2 1549.74     438 1552.89   496.5 1569.61
#Mann= 3 , 0 , 0
       0      .1       0   401.2    .045       0   416.2      .1       0
Bank Sta=401.2,416.2
XS Rating Curve= 0 ,0
Exp/Cntr=0.3,0.1

Type RM Length L Ch R = 1 ,12163.4 ,405.6,406.3,408.4
XS GIS Cut Line= 3
     1771528.427       138464.66     1771554.925      138561.082
     1771731.444      138650.608
#Sta/Elev= 24
      10 1583.44      20 1580.36      30 1577.38      40 1574.48      50 1571.81
      60 1569.56     100 1561.53   119.8 1554.84   129.7 1551.34   149.5 1543.69
   159.4 1540.94   161.8 1540.83   169.3 1540.48   176.8 1542.07   179.2 1542.58
   189.1 1546.23     199 1550.18   218.8 1557.54   248.4 1568.98   258.3 1573.01
   268.2 1577.34   278.1 1582.25     288 1587.79   297.9 1593.66
#Mann= 3 , 0 , 0
       0      .1       0   161.8    .045       0   176.8      .1       0
Bank Sta=161.8,176.8
XS Rating Curve= 0 ,0
Exp/Cntr=0.3,0.1

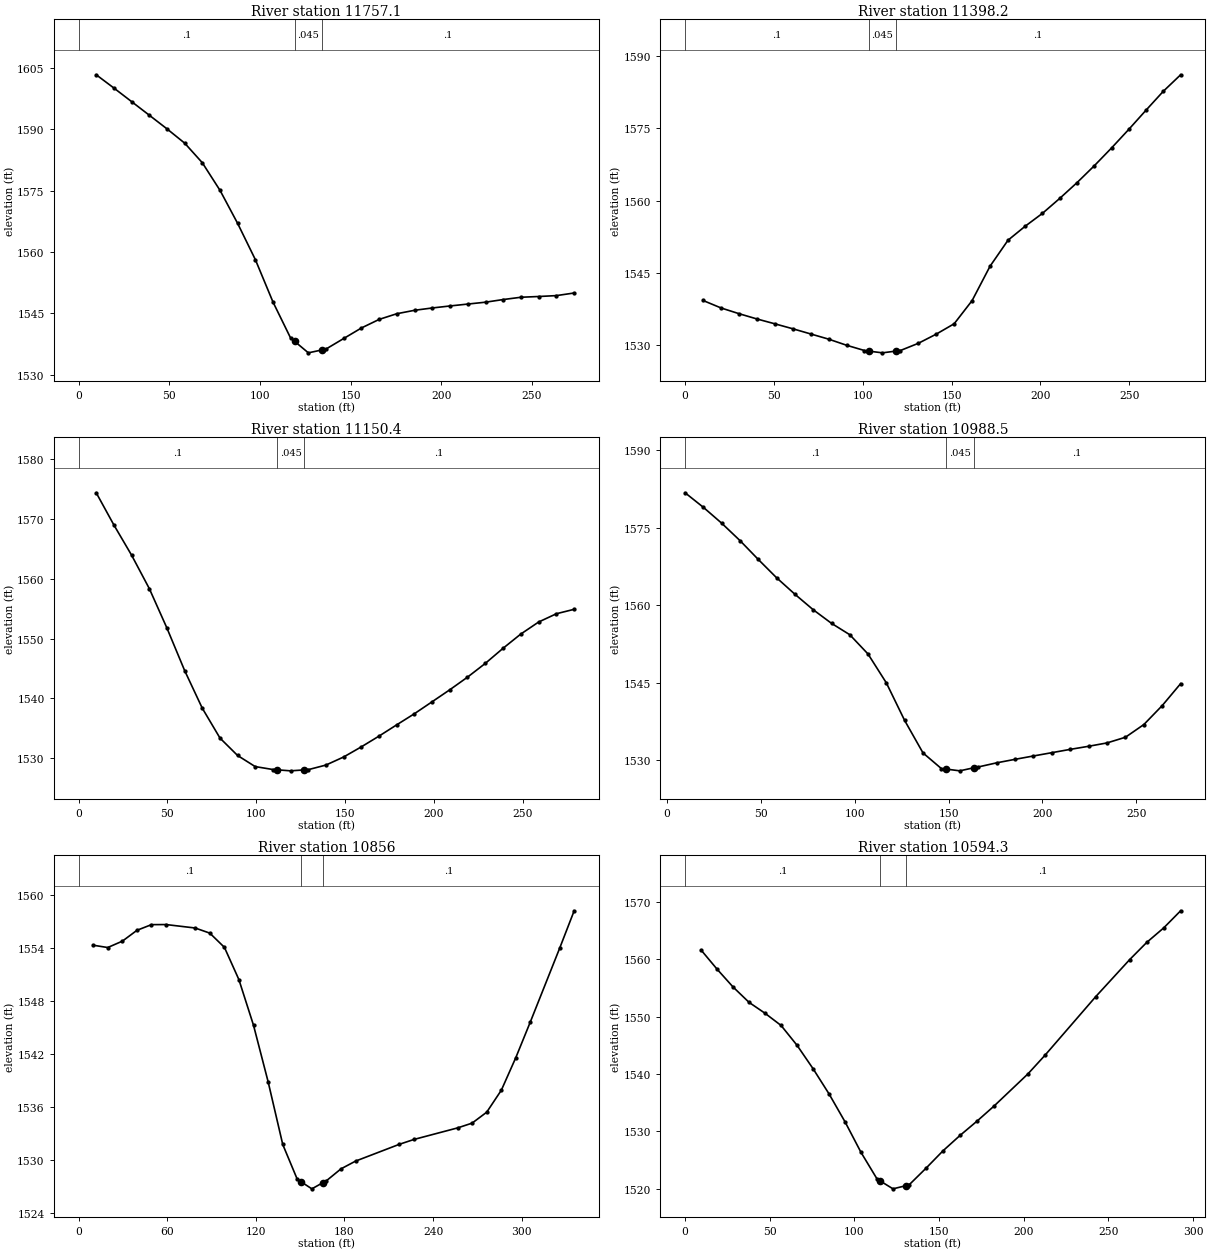
Type RM Length L Ch R = 1 ,11757.1 ,358.3,358.9,358.1
XS GIS Cut Line= 3
     1771238.962      138816.709     1771358.807      138881.919
     1771474.478      138955.061
#Sta/Elev= 30
     9.7 1603.35    19.5 1600.09    29.2 1596.79      39 1593.45    48.7 1590.13
    58.5 1586.62    68.2 1581.84      78 1575.06    87.7 1566.99    97.5  1558.1
   107.2 1547.75   116.9 1538.96   119.2 1538.11   126.7 1535.33   134.2 1536.04
   136.4 1536.25   146.2 1538.84     156 1541.42   165.8 1543.52   175.5  1544.9
   185.3 1545.74   195.1 1546.31   204.9  1546.8   214.6 1547.26   224.4 1547.72
   234.2 1548.37     244 1548.93   253.7 1549.11   263.5 1549.33   273.3 1549.97
#Mann= 3 , 0 , 0
       0      .1       0   119.2    .045       0   134.2      .1       0
Bank Sta=119.2,134.2
XS Rating Curve= 0 ,0
Exp/Cntr=0.3,0.1

Type RM Length L Ch R = 1 ,11398.2 ,238.5,247.8,257
XS GIS Cut Line= 3
     1771151.366      139162.899       1771309.1       139253.27
     1771370.055      139328.937
#Sta/Elev= 30
    10.1 1539.23    20.2 1537.68    30.3 1536.49    40.4 1535.39    50.5 1534.38
    60.6 1533.35    70.7 1532.27    80.8 1531.19    90.9 1529.92     101 1528.82
   103.6 1528.69   111.1 1528.34   118.6  1528.7   121.2 1528.82   131.3 1530.32
   141.4 1532.23   151.5 1534.39   161.6 1539.21   171.7 1546.36   181.8 1551.76
   191.5 1554.68   201.2 1557.35   210.9 1560.45   220.7 1563.75   230.4 1567.25
   240.1 1570.95   249.8 1574.81   259.5  1578.8   269.2 1582.72     279 1586.17
#Mann= 3 , 0 , 0
       0      .1       0   103.6    .045       0   118.6      .1       0
Bank Sta=103.6,118.6
XS Rating Curve= 0 ,0
Exp/Cntr=0.3,0.1

Type RM Length L Ch R = 1 ,11150.4 ,166.7,162,156.6
XS GIS Cut Line= 3
     1770981.931      139223.606     1771100.387      139383.383
     1771160.992      139435.724
#Sta/Elev= 30
     9.9 1574.32    19.9 1568.92    29.8 1563.92    39.8 1558.33    49.7 1551.76
    59.7 1544.65    69.6 1538.39    79.6 1533.39    89.5 1530.49    99.4 1528.64
   109.4 1528.15   111.8  1528.1   119.3 1527.93   126.8 1528.08   129.3 1528.13
   139.2 1528.89   149.2 1530.24   159.1 1531.92   169.1 1533.72     179 1535.59
     189 1537.45   198.9 1539.43   208.9 1541.44   218.9 1543.55   228.9 1545.84
   238.9 1548.36   248.9 1550.74     259 1552.76     269 1554.14     279 1554.88
#Mann= 3 , 0 , 0
       0      .1       0   111.8    .045       0   126.8      .1       0
Bank Sta=111.8,126.8
XS Rating Curve= 0 ,0
Exp/Cntr=0.3,0.1

Type RM Length L Ch R = 1 ,10988.5 ,135.9,132.4,129.6
XS GIS Cut Line= 3
     1770829.419      139323.909     1770926.412      139419.773
     1771032.566      139506.729
#Sta/Elev= 30
     9.7  1581.8    19.5 1578.96    29.2  1575.9      39 1572.51    48.7 1568.87
    58.4 1565.34    68.2 1562.13    77.9 1559.14    87.7 1556.49    97.4 1554.29
   107.1 1550.56   116.9 1544.94   126.6 1537.69   136.4 1531.38   146.2 1528.34
   148.5 1528.26     156 1527.91   163.5 1528.51   165.8 1528.66   175.6 1529.46
   185.4 1530.14   195.2 1530.79     205 1531.43   214.8 1532.07   224.6 1532.67
   234.4 1533.32   244.2 1534.42     254 1536.88   263.8 1540.56   273.6 1544.81
#Mann= 3 , 0 , 0
     9.7      .1       0   148.5    .045       0   163.5      .1       0
Bank Sta=148.5,163.5
XS Rating Curve= 0 ,0
Exp/Cntr=0.3,0.1

Type RM Length L Ch R = 1 ,10856   ,258.2,261.7,267.1
XS GIS Cut Line= 2
     1770728.492      139452.253     1771012.234      139631.313
#Sta/Elev= 30
     9.9 1554.36    19.7  1554.1    29.6 1554.82    39.5 1556.05    49.3 1556.69
    59.2  1556.7    78.9 1556.31    88.8 1555.73    98.7 1554.12   108.5 1550.47
   118.4  1545.3   128.3  1538.9   138.2  1531.8     148 1527.87   150.4  1527.6
   157.9 1526.78   165.4 1527.48   167.8  1527.7   177.6 1529.04   187.5 1529.92
   217.1 1531.82     227 1532.37   256.6 1533.68   266.4 1534.22   276.3 1535.46
   286.2 1537.95     296 1541.64   305.9 1545.71   325.6 1553.99   335.5 1558.26
#Mann= 3 , 0 , 0
       0      .1       0   150.4    .045       0   165.4      .1       0
Bank Sta=150.4,165.4
XS Rating Curve= 0 ,0
Exp/Cntr=0.3,0.1

Type RM Length L Ch R = 1 ,10594.3 ,490.7,488.8,495.4
XS GIS Cut Line= 3
     1770579.426      139550.865     1770680.145      139636.614
      1770777.17      139764.381
#Sta/Elev= 28
     9.4 1561.59    18.9 1558.24    28.3 1555.15    37.8 1552.46    47.2 1550.57
    56.7 1548.44    66.1    1545    75.6 1540.91      85 1536.54    94.5 1531.65
   103.9 1526.35   113.4 1521.71   115.3 1521.36   122.8    1520   130.3 1520.54
   132.3 1520.69   142.3 1523.59   152.3 1526.61   162.4  1529.3   172.4 1531.78
   182.4 1534.39   202.5 1540.01   212.5 1543.23   242.6 1553.48   262.6 1559.91
   272.7 1562.91   282.7 1565.43   292.7 1568.41
#Mann= 3 , 0 , 0
       0      .1       0   115.3    .045       0   130.3      .1       0
Bank Sta=115.3,130.3
XS Rating Curve= 0 ,0
Exp/Cntr=0.3,0.1

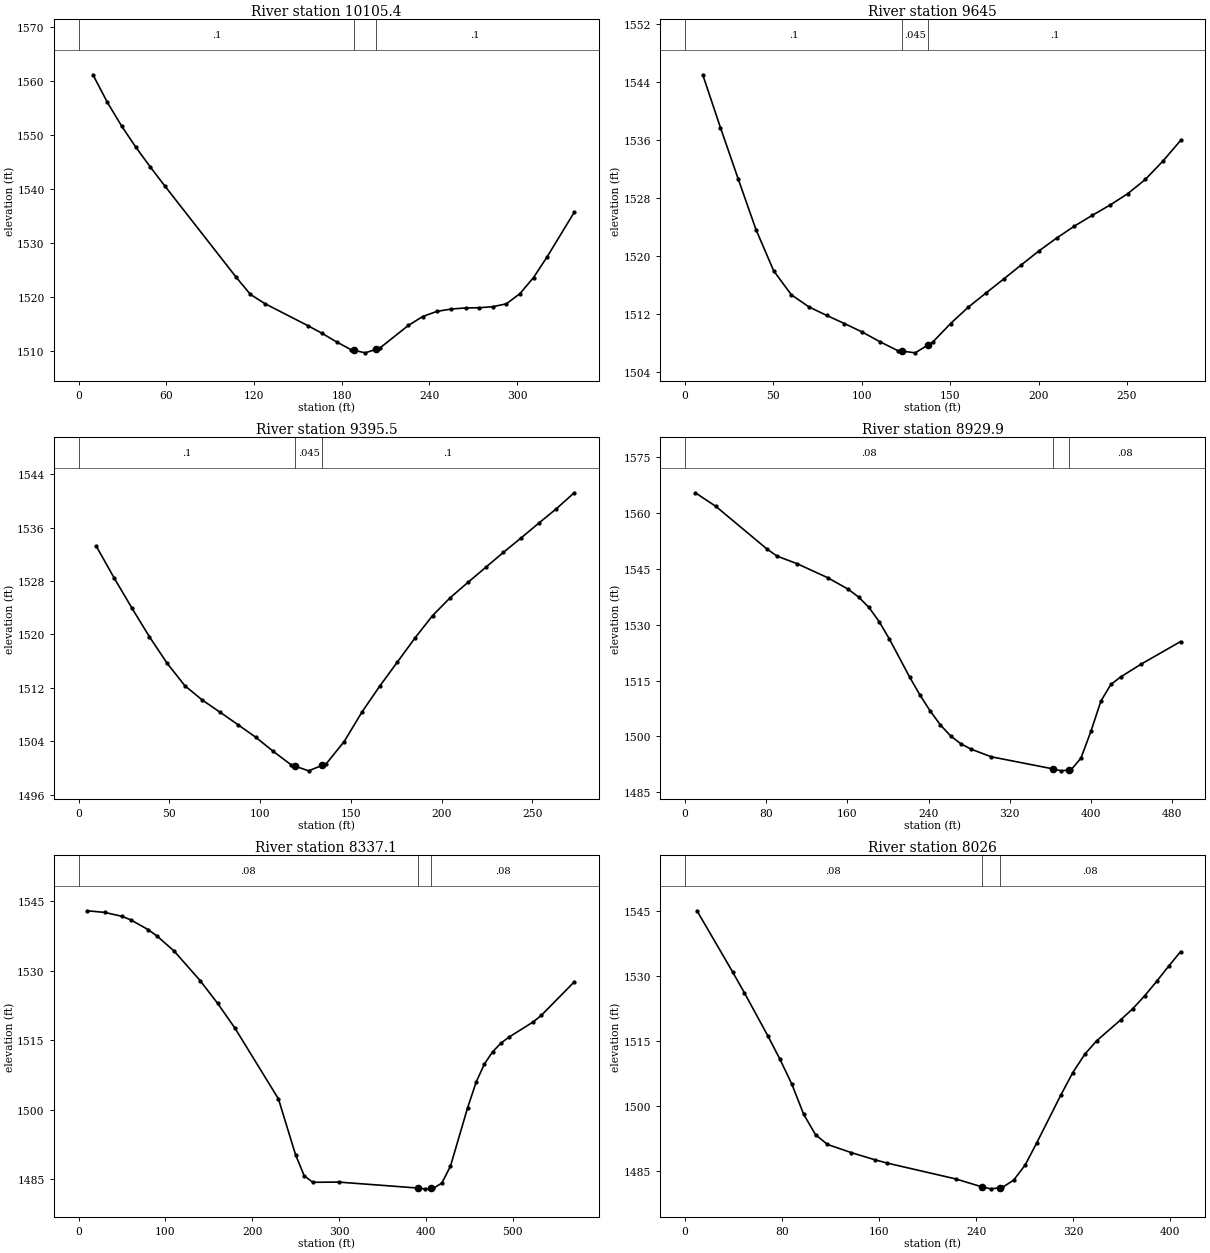
Type RM Length L Ch R = 1 ,10105.4 ,462.4,460.5,465.8
XS GIS Cut Line= 4
     1770184.424      139654.729     1770203.707      139760.788
     1770300.124      139884.753     1770356.597      139932.961
#Sta/Elev= 29
     9.8 1561.09    19.6 1556.02    29.4 1551.62    39.2 1547.68      49 1544.06
    58.8  1540.6   107.8 1523.66   117.6 1520.47   127.4 1518.79   156.9  1514.7
   166.7 1513.27   176.5  1511.7   186.3 1510.28   188.6 1510.14   196.1 1509.68
   203.6 1510.33     206 1510.54   225.6 1514.74   235.4 1516.39   245.2 1517.35
     255 1517.78   264.8 1517.98   274.1 1518.02   283.4 1518.21   292.7 1518.74
     302 1520.63   311.3  1523.6   320.5 1527.39   339.1 1535.65
#Mann= 3 , 0 , 0
       0      .1       0   188.6    .045       0   203.6      .1       0
Bank Sta=188.6,203.6
XS Rating Curve= 0 ,0
Exp/Cntr=0.3,0.1

Type RM Length L Ch R = 1 ,9645    ,253.6,249.5,245.3
XS GIS Cut Line= 2
     1769829.057      139904.036     1769946.135      140158.853
#Sta/Elev= 30
      10 1544.98      20 1537.69      30 1530.63    40.1 1523.61    50.1 1517.92
    60.1  1514.6    70.1 1512.92    80.1 1511.75    90.1 1510.63   100.2 1509.46
   110.2 1508.12   120.2  1506.9   122.7 1506.82   130.2 1506.58   137.7  1507.7
   140.2 1508.08   150.2 1510.62   160.2 1512.88   170.3 1514.85   180.3 1516.78
   190.3 1518.74   200.3 1520.67   210.3 1522.44   220.3 1524.08   230.4 1525.57
   240.4 1526.98   250.4 1528.55   260.4 1530.52   270.4 1533.07   280.4 1535.92
#Mann= 3 , 0 , 0
       0      .1       0   122.7    .045       0   137.7      .1       0
Bank Sta=122.7,137.7
XS Rating Curve= 0 ,0
Exp/Cntr=0.3,0.1

Type RM Length L Ch R = 1 ,9395.5  ,446.7,465.6,484.5
XS GIS Cut Line= 3
     1769598.579      140044.866     1769677.473      140156.257
     1769756.367      140267.648
#Sta/Elev= 30
     9.8 1533.17    19.5 1528.48    29.3 1523.96      39 1519.64    48.8 1515.65
    58.5 1512.31    68.2 1510.14      78 1508.32    87.7 1506.48    97.5  1504.6
   107.2 1502.47     117 1500.47   119.2 1500.26   126.7 1499.55   134.2 1500.38
   136.5 1500.64   146.3 1503.94     156 1508.32   165.8 1512.21   175.5 1515.81
   185.2 1519.42     195 1522.81   204.7 1525.49   214.5 1527.79   224.2 1530.02
     234 1532.28   243.7 1534.43   253.5 1536.66   263.2 1538.82     273 1541.21
#Mann= 3 , 0 , 0
       0      .1       0   119.2    .045       0   134.2      .1       0
Bank Sta=119.2,134.2
XS Rating Curve= 0 ,0
Exp/Cntr=0.3,0.1

Type RM Length L Ch R = 1 ,8929.9  ,616.8,592.8,555.2
XS GIS Cut Line= 3
     1769304.987       139981.08     1769309.119      140273.087
     1769266.711      140465.024
#Sta/Elev= 30
    10.1 1565.43    30.2 1561.81    80.6 1550.36    90.6 1548.44   110.8 1546.35
     141 1542.58   161.1 1539.49   171.2  1537.4   181.3 1534.64   191.3 1530.86
   201.4 1526.18   221.5  1515.9   231.6 1511.12   241.7 1506.83   251.8 1503.09
   261.8 1500.14   271.9 1498.05     282 1496.59   301.9 1494.55   363.2 1491.28
   370.7 1490.78   378.2 1490.98   380.5 1491.04   390.3 1494.19   400.1 1501.36
     410 1509.52   419.8 1513.96   429.6 1516.01   449.3 1519.37   488.6  1525.5
#Mann= 3 , 0 , 0
       0     .08       0   363.2    .045       0   378.2     .08       0
Bank Sta=363.2,378.2
XS Rating Curve= 0 ,0
Exp/Cntr=0.3,0.1

Type RM Length L Ch R = 1 ,8337.1  ,313.3,311.1,303.4
XS GIS Cut Line= 4
     1768866.263      140131.305     1768910.339      140357.197
     1769105.928      140474.275     1769209.233      140519.729
#Sta/Elev= 30
      10 1542.92      30 1542.57      50 1541.72      60 1540.97    80.1 1538.85
    90.1 1537.51   110.1 1534.21   140.1 1527.83   160.1 1522.95   180.1 1517.59
   230.2 1502.33     250 1490.23   259.9 1485.73   269.8 1484.31   299.5 1484.36
   391.1 1483.07   398.6  1482.9   406.1 1482.98   408.5    1483   418.5 1484.14
   428.4 1487.76   448.2 1500.39   458.1 1505.97   467.5 1509.82   476.9 1512.45
   486.3  1514.3   495.7 1515.63   523.9 1518.94   533.3 1520.37     571 1527.56
#Mann= 3 , 0 , 0
       0     .08       0   391.1    .045       0   406.1     .08       0
Bank Sta=391.1,406.1
XS Rating Curve= 0 ,0
Exp/Cntr=0.3,0.1

Type RM Length L Ch R = 1 ,8026    ,369.2,379.7,389.5
XS GIS Cut Line= 4
     1768738.166      140492.181     1768864.885      140599.617
     1768975.076       140656.09     1769093.532      140660.222
#Sta/Elev= 30
     9.8 1545.16    39.1 1531.05    48.9 1526.17    68.4 1516.12    78.2  1510.8
      88 1505.04    97.7  1498.1   107.5 1493.35   117.3  1491.1   136.8 1489.22
   156.4 1487.55   166.1 1486.81   223.3  1483.1   244.4  1481.3   251.9 1480.82
   259.4 1481.06   261.4 1481.13   270.9 1482.84   280.4 1486.36     290 1491.53
   309.7  1502.5   319.6 1507.72   329.5 1511.97   339.3 1515.08   359.1 1519.93
     369  1522.5   378.8 1525.46   388.7 1528.82   398.6 1532.34   408.5 1535.71
#Mann= 3 , 0 , 0
       0     .08       0   244.4    .045       0   259.4     .08       0
Bank Sta=244.4,259.4
XS Rating Curve= 0 ,0
Exp/Cntr=0.3,0.1

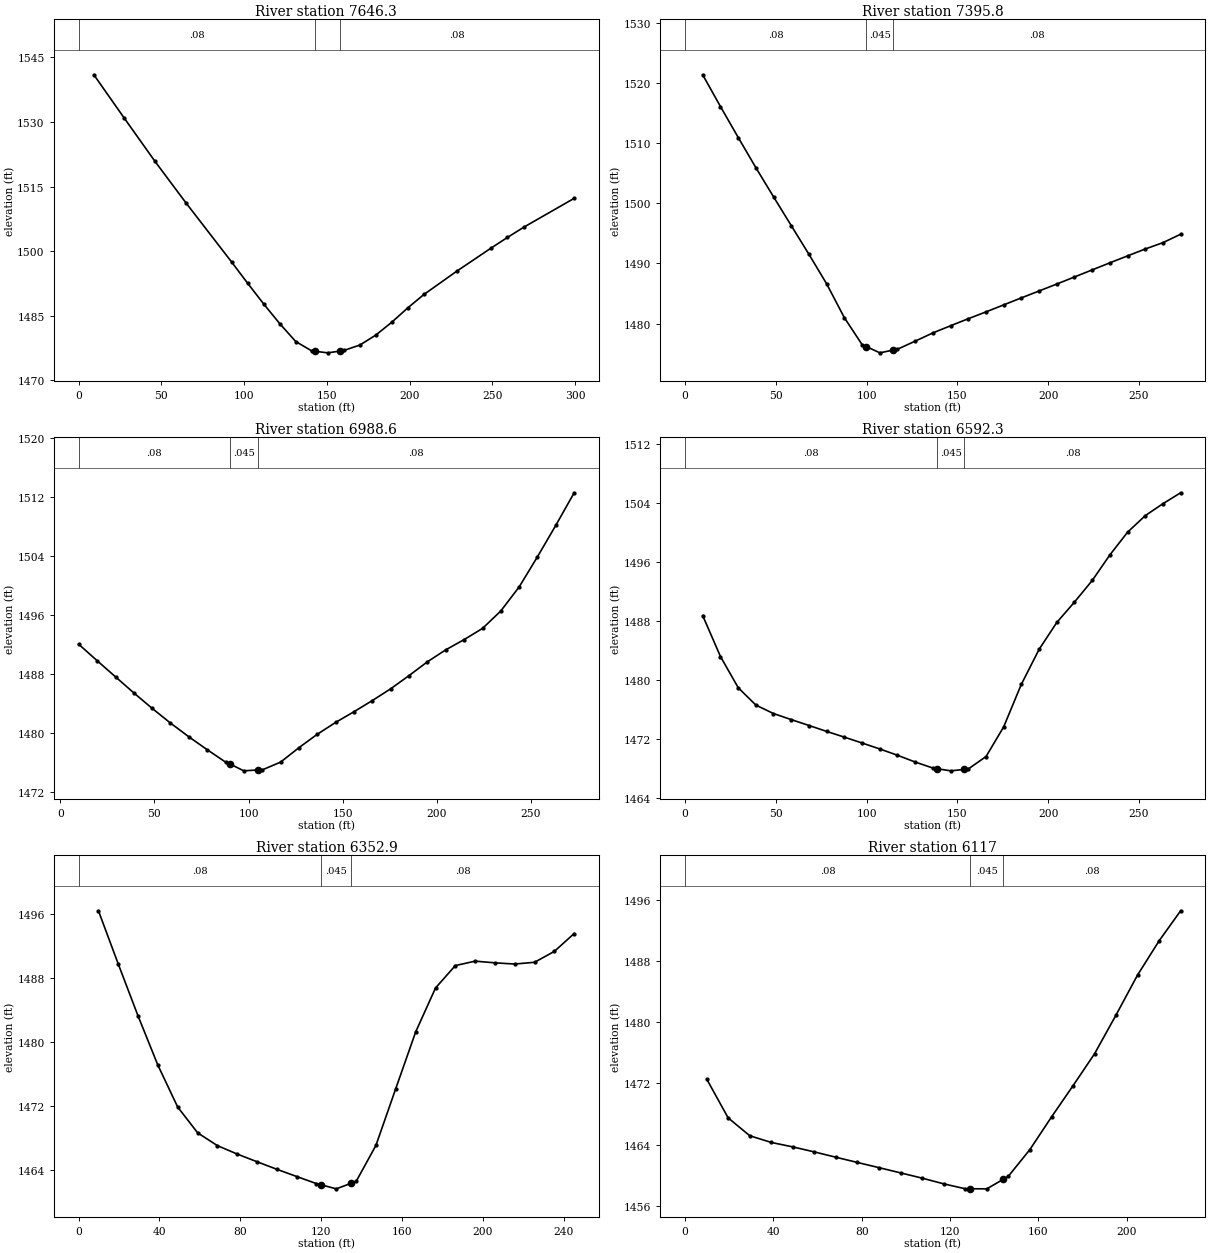
Type RM Length L Ch R = 1 ,7646.3  ,250.4,250.5,250.7
XS GIS Cut Line= 4
     1768590.785      140675.374     1768629.352      140759.394
     1768698.221      140853.057     1768782.242      140887.492
#Sta/Elev= 24
     9.2 1540.94    27.7 1530.81    46.2 1520.81    64.7 1511.29    92.4 1497.51
   102.1 1492.57   111.8 1487.76   121.5 1483.19   131.2 1479.02   140.9 1476.84
   143.1 1476.74   150.6 1476.39   158.1 1476.81   160.3 1476.94     170  1478.2
   179.6 1480.51   189.3 1483.51     199 1486.85   208.7 1489.94   228.9 1495.44
   249.1 1500.66   259.2 1503.19   269.2 1505.59   299.5 1512.26
#Mann= 3 , 0 , 0
       0     .08       0   143.1    .045       0   158.1     .08       0
Bank Sta=143.1,158.1
XS Rating Curve= 0 ,0
Exp/Cntr=0.3,0.1

Type RM Length L Ch R = 1 ,7395.8  ,410.3,407.2,404
XS GIS Cut Line= 3
     1768392.351      140858.923     1768472.844      140969.164
     1768553.338      141079.405
#Sta/Elev= 30
     9.7 1521.35    19.5 1516.06    29.3 1510.91      39  1505.9    48.8 1501.03
    58.5 1496.27    68.2 1491.52      78 1486.59    87.7 1480.99    97.5  1476.5
    99.8 1476.18   107.3 1475.13   114.8  1475.6     117 1475.73   126.8 1477.08
   136.5 1478.44   146.3 1479.64     156  1480.8   165.8 1481.94   175.5  1483.1
   185.2 1484.26     195 1485.41   204.8 1486.57   214.5 1487.74   224.3 1488.92
     234 1490.09   243.8 1491.25   253.5 1492.39   263.3 1493.45     273 1494.85
#Mann= 3 , 0 , 0
       0     .08       0    99.8    .045       0   114.8     .08       0
Bank Sta=99.8,114.8
XS Rating Curve= 0 ,0
Exp/Cntr=0.3,0.1

Type RM Length L Ch R = 1 ,6988.6  ,379.7,396.3,412.9
XS GIS Cut Line= 3
     1768075.897      141123.604     1768171.575      141220.959
     1768267.252      141318.315
#Sta/Elev= 30
     9.7 1492.03    19.5  1489.8    29.3  1487.6      39 1485.43    48.7 1483.34
    58.5 1481.33    68.2 1479.48      78 1477.72    87.8 1476.03      90 1475.79
   97.46 1474.85     105 1474.97   107.2 1474.97     117 1476.03   126.8    1478
   136.5 1479.81   146.2 1481.41     156 1482.87   165.8 1484.39   175.5 1485.98
   185.2 1487.76     195 1489.64   204.8 1491.27   214.5 1492.65   224.3 1494.17
     234 1496.53   243.8 1499.81   253.5 1503.89   263.3 1508.18     273 1512.57
#Mann= 3 , 0 , 0
     9.7     .08       0      90    .045       0     105     .08       0
Bank Sta=90,105
XS Rating Curve= 0 ,0
Exp/Cntr=0.3,0.1

Type RM Length L Ch R = 1 ,6592.3  ,248.4,239.5,230.5
XS GIS Cut Line= 3
     1767803.068      141202.971     1767809.129      141339.336
      1767815.19      141475.701
#Sta/Elev= 30
     9.7 1488.69    19.5 1483.14    29.3 1478.91      39 1476.57    48.7 1475.42
    58.5  1474.6    68.3  1473.8      78    1473    87.8 1472.22    97.5 1471.43
   107.3 1470.62     117 1469.77   126.8 1468.85   136.5 1468.04   138.8 1467.95
   146.3 1467.66   153.8 1467.85     156 1467.91   165.8  1469.6   175.5 1473.61
   185.2 1479.36     195 1484.11   204.8 1487.77   214.5 1490.52   224.3 1493.45
     234 1496.91   243.8    1500   253.5 1502.23   263.3 1503.86     273 1505.33
#Mann= 3 , 0 , 0
       0     .08       0   138.8    .045       0   153.8     .08       0
Bank Sta=138.8,153.8
XS Rating Curve= 0 ,0
Exp/Cntr=0.3,0.1

Type RM Length L Ch R = 1 ,6352.9  ,230.9,235.9,240.9
XS GIS Cut Line= 2
     1767526.064      141281.425     1767630.745      141503.184
#Sta/Elev= 27
     9.8 1496.39    19.6 1489.75    29.4 1483.26    39.2 1477.12      49 1471.89
    58.9 1468.66    68.7 1467.06    78.5 1466.01    88.3 1465.05    98.1 1464.11
   107.9 1463.21   117.7 1462.32     120 1462.17   127.5 1461.67     135 1462.38
   137.3 1462.59   147.1 1467.09   156.9 1474.17   166.8 1481.28   176.6 1486.75
   186.4 1489.55   196.2  1490.1     206 1489.89   215.8 1489.74   225.6 1489.96
   235.4 1491.32   245.2 1493.55
#Mann= 3 , 0 , 0
       0     .08       0     120    .045       0     135     .08       0
Bank Sta=120,135
XS Rating Curve= 0 ,0
Exp/Cntr=0.3,0.1

Type RM Length L Ch R = 1 ,6117    ,277.7,281.6,285.5
XS GIS Cut Line= 2
     1767347.003      141369.577     1767396.589      141588.582
#Sta/Elev= 25
     9.8 1472.57    19.5  1467.5    29.3 1465.16    39.1 1464.28    48.8  1463.7
    58.6 1463.04    68.3 1462.35    78.1 1461.66    87.9 1460.98    97.6  1460.3
   107.4 1459.61   117.2 1458.86   126.9 1458.22   129.2 1458.22   136.7 1458.21
   144.2 1459.47   146.4 1459.84   156.2 1463.35     166 1467.62   175.7 1471.69
   185.5 1475.89   195.3    1481     205 1486.21   214.8  1490.7   224.5 1494.61
#Mann= 3 , 0 , 0
       0     .08       0   129.2    .045       0   144.2     .08       0
Bank Sta=129.2,144.2
XS Rating Curve= 0 ,0
Exp/Cntr=0.3,0.1

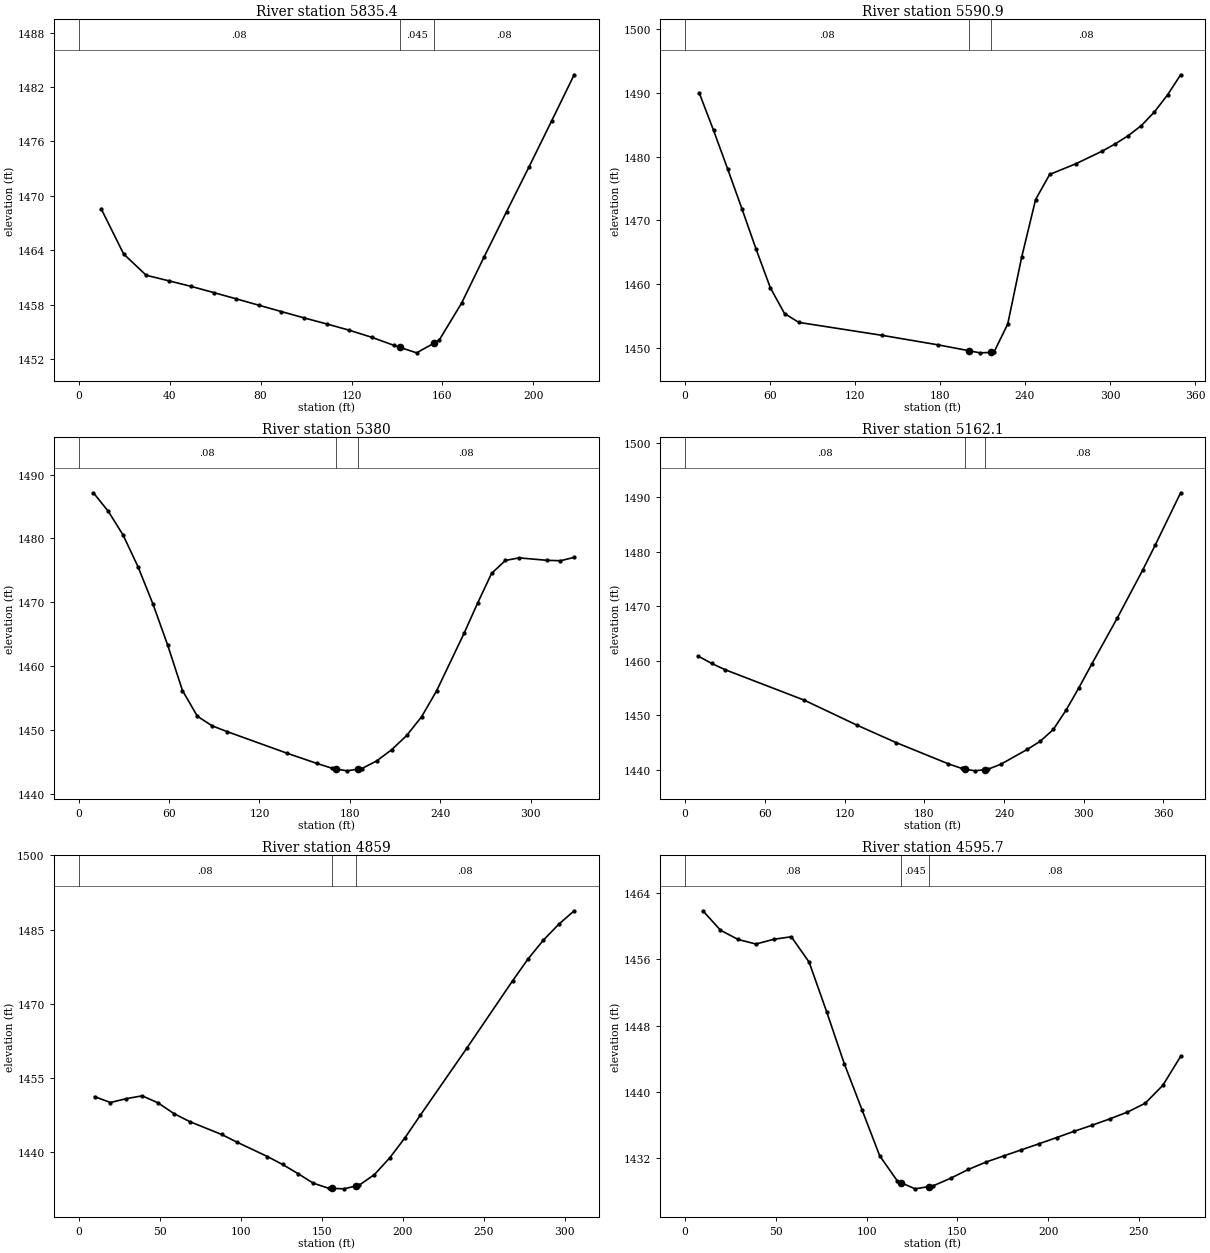
Type RM Length L Ch R = 1 ,5835.4  ,239.6,244.5,249.5
XS GIS Cut Line= 2
     1767092.186      141410.899     1767103.205      141628.527
#Sta/Elev= 24
     9.9 1468.59    19.8  1463.6    29.7 1461.26    39.6 1460.65    49.5 1460.03
    59.4 1459.35    69.3 1458.66    79.2 1457.96    89.1 1457.26      99 1456.57
     109  1455.9   118.9 1455.21   128.8 1454.43   138.7 1453.53   141.1 1453.33
   148.6 1452.71   156.1 1453.75   158.5 1454.09   168.4 1458.19   178.3 1463.28
   188.2 1468.28   198.1 1473.23     208 1478.27   217.9 1483.35
#Mann= 3 , 0 , 0
       0     .08       0   141.1    .045       0   156.1     .08       0
Bank Sta=141.1,156.1
XS Rating Curve= 0 ,0
Exp/Cntr=0.3,0.1

Type RM Length L Ch R = 1 ,5590.9  ,222.7,210.9,198
XS GIS Cut Line= 4
     1766920.203      141343.894     1766887.887      141417.368
     1766854.231      141591.232     1766887.887      141677.489
#Sta/Elev= 26
      10 1489.97    20.1  1484.1    30.1 1478.02    40.1 1471.82    50.2 1465.41
    60.2 1459.39    70.2 1455.35    80.3 1453.96   139.3 1451.92   178.7 1450.43
   200.7  1449.5   208.2 1449.18   215.7 1449.24     218 1449.25   227.8 1453.69
   237.7 1464.24   247.5 1473.25   257.4 1477.18   275.9 1478.86   294.4 1480.83
   303.7 1481.98   312.9 1483.27   322.2 1484.86   331.4    1487   340.7 1489.69
   349.9 1492.83
#Mann= 3 , 0 , 0
       0     .08       0   200.7    .045       0   215.7     .08       0
Bank Sta=200.7,215.7
XS Rating Curve= 0 ,0
Exp/Cntr=0.3,0.1

Type RM Length L Ch R = 1 ,5380    ,225.6,217.9,211.1
XS GIS Cut Line= 3
     1766639.025      141267.651     1766696.876       141494.92
     1766732.688       141578.94
#Sta/Elev= 30
     9.8 1487.15    19.7 1484.24    29.5 1480.53    39.4 1475.56    49.2 1469.79
      59 1463.34    68.9 1456.16    78.8 1452.13    88.7 1450.62    98.6 1449.72
   138.3 1446.34   158.1 1444.74   168.1 1443.99   170.5 1443.89     178 1443.58
   185.5 1443.85   187.9 1443.93   197.8 1445.14   207.7 1446.89   217.7 1449.12
   227.6 1452.07   237.5 1456.11   255.8 1465.16   264.9 1469.95     274 1474.52
   283.2 1476.55   292.3 1476.95   310.6 1476.57   319.7  1476.5   328.8 1477.03
#Mann= 3 , 0 , 0
       0     .08       0   170.5    .045       0   185.5     .08       0
Bank Sta=170.5,185.5
XS Rating Curve= 0 ,0
Exp/Cntr=0.3,0.1

Type RM Length L Ch R = 1 ,5162.1  ,277.3,303.1,328.9
XS GIS Cut Line= 4
     1766411.756      141355.803     1766414.511      141445.334
     1766535.721      141588.582      1766583.93      141671.225
#Sta/Elev= 23
      10 1460.84    19.9 1459.52    29.9 1458.38    89.6 1452.77   129.1  1448.2
   158.7 1444.98   198.2 1441.06   208.1 1440.23   210.5 1440.12     218 1439.78
   225.5    1440   227.8 1440.06   237.7    1441   257.5 1443.72   267.3 1445.22
   277.2 1447.41   286.8 1450.98   296.4 1455.07   305.9 1459.34   325.1  1467.8
   344.2 1476.59   353.8 1481.26   372.9 1490.86
#Mann= 3 , 0 , 0
       0     .08       0   210.5    .045       0   225.5     .08       0
Bank Sta=210.5,225.5
XS Rating Curve= 0 ,0
Exp/Cntr=0.3,0.1

Type RM Length L Ch R = 1 ,4859    ,284.8,263.4,241.9
XS GIS Cut Line= 4
     1766287.791      141450.843     1766286.414      141538.996
     1766236.828      141640.923     1766251.979      141744.227
#Sta/Elev= 28
     9.8 1451.28    19.6 1450.08    29.4 1450.86    39.2 1451.43      49 1450.02
    58.8 1447.85    68.6 1446.22    88.2 1443.64    97.6  1442.1   116.5 1439.18
   125.9 1437.57   135.4 1435.73   144.8  1433.8   154.3 1432.77   156.2 1432.75
   163.7 1432.65   171.2 1433.23   173.2 1433.39   182.6 1435.53   192.1 1438.92
   201.5 1442.98     211 1447.55   239.5    1461     268 1474.71   277.4 1479.06
   286.9 1482.88   296.4 1486.08   305.9  1488.8
#Mann= 3 , 0 , 0
       0     .08       0   156.2    .045       0   171.2     .08       0
Bank Sta=156.2,171.2
XS Rating Curve= 0 ,0
Exp/Cntr=0.3,0.1

Type RM Length L Ch R = 1 ,4595.7  ,379.9,388.3,396.8
XS GIS Cut Line= 3
     1765953.194      141504.033     1766017.108      141624.645
     1766081.022      141745.257
#Sta/Elev= 30
     9.8 1461.88    19.5 1459.53    29.2 1458.41      39 1457.86    48.8 1458.43
    58.5 1458.74    68.3 1455.68      78 1449.66    87.7 1443.39    97.5  1437.8
   107.2 1432.26     117 1429.19   119.2 1428.98   126.7 1428.26   134.2 1428.53
   136.5 1428.61   146.3 1429.54     156  1430.6   165.7 1431.49   175.5 1432.24
   185.2 1432.97     195 1433.71   204.7 1434.46   214.5 1435.23   224.2 1435.95
     234 1436.72   243.7 1437.54   253.5 1438.61   263.2 1440.78     273 1444.27
#Mann= 3 , 0 , 0
       0     .08       0   119.2    .045       0   134.2     .08       0
Bank Sta=119.2,134.2
XS Rating Curve= 0 ,0
Exp/Cntr=0.3,0.1

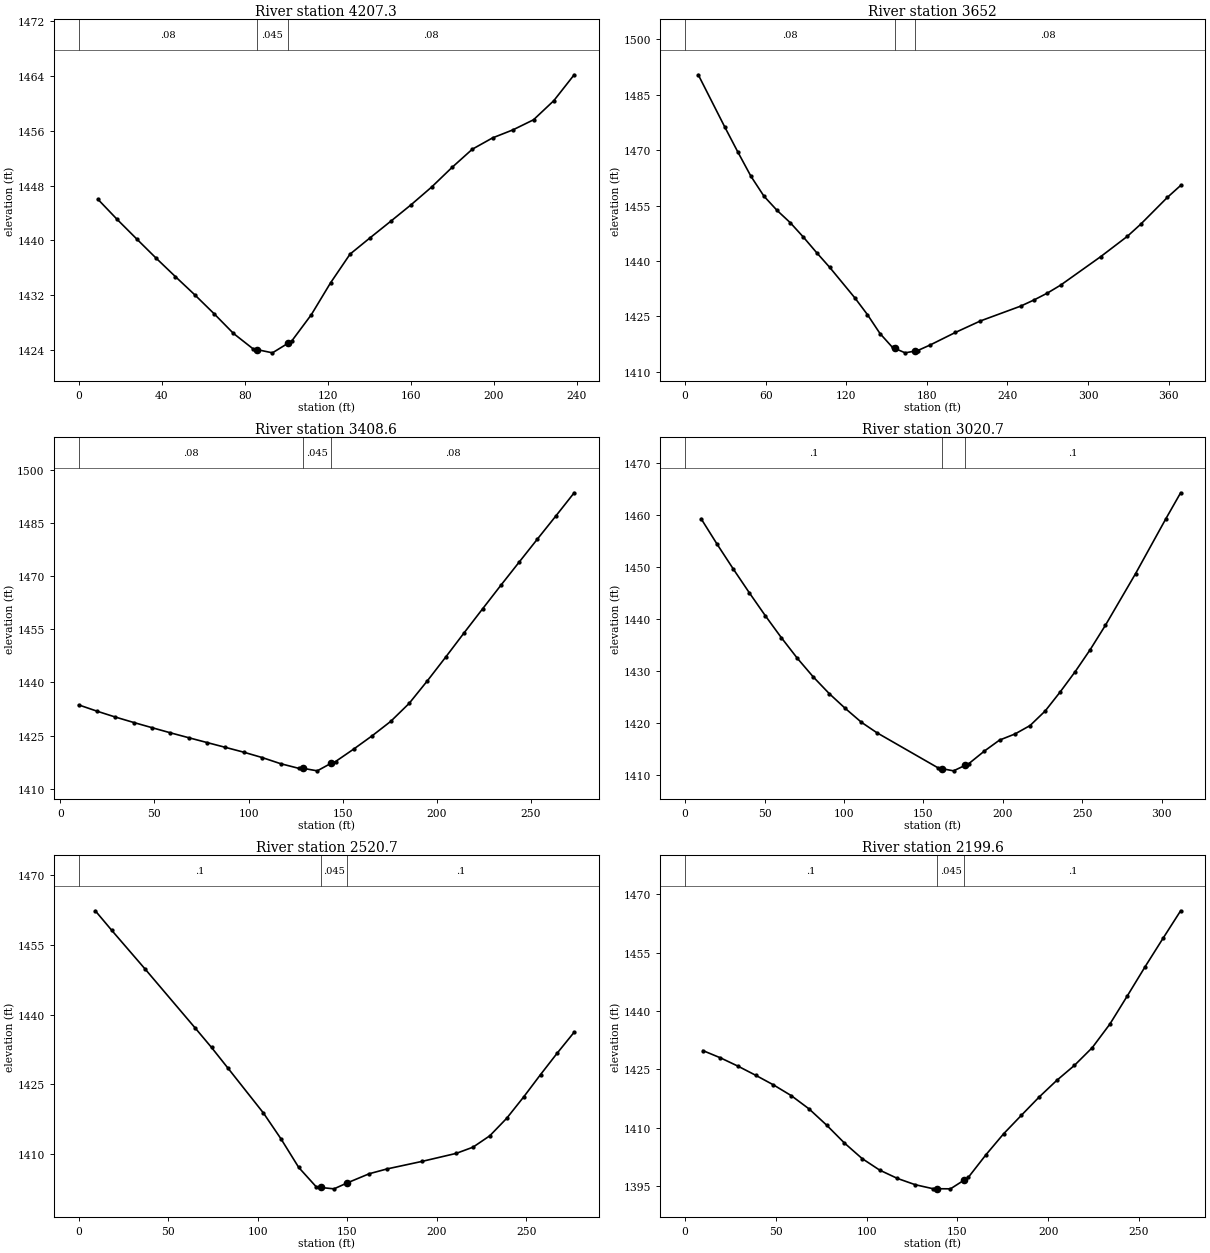
Type RM Length L Ch R = 1 ,4207.3  ,571.7,555.4,539
XS GIS Cut Line= 4
     1765727.194      141764.888     1765736.836      141819.983
       1765745.1      141894.362     1765847.027      141930.175
#Sta/Elev= 27
     9.3    1446    18.6 1443.05      28  1440.2    37.3 1437.41    46.6 1434.71
    55.9 1432.06    65.3 1429.27    74.6  1426.4      84 1424.16    85.9 1424.04
    93.4 1423.56   100.9 1424.96   102.7 1425.29   112.1 1429.12   121.4 1433.79
   130.8 1437.99   140.6 1440.41   150.4 1442.79   160.2  1445.2   170.1 1447.79
   179.9 1450.65   189.7 1453.32   199.5 1454.98   209.3 1456.15   219.2 1457.62
     229 1460.42   238.8  1464.2
#Mann= 3 , 0 , 0
       0     .08       0    85.9    .045       0   100.9     .08       0
Bank Sta=85.9,100.9
XS Rating Curve= 0 ,0
Exp/Cntr=0.3,0.1

Type RM Length L Ch R = 1 ,3652    ,238.5,243.3,248.5
XS GIS Cut Line= 4
     1765206.541       141927.42     1765245.108      142027.969
     1765329.129      142102.348     1765473.755       142138.16
#Sta/Elev= 30
     9.8 1490.42    29.4 1476.37    39.2 1469.54      49 1462.93    58.7 1457.53
    68.5 1453.66    78.3 1450.34    88.1 1446.42    97.9 1442.24   107.7 1438.22
   126.4 1429.96   135.7 1425.46   145.1 1420.31   154.4 1416.55   156.3 1416.26
   163.8 1415.08   171.3 1415.57   173.1 1415.69   182.5 1417.22   201.2  1420.6
   219.9 1423.73   249.7 1427.72   259.6 1429.38   269.6 1431.25   279.5 1433.41
   309.3 1441.12   329.2 1446.64   339.1 1449.91     359 1457.19   368.9 1460.43
#Mann= 3 , 0 , 0
       0     .08       0   156.3    .045       0   171.3     .08       0
Bank Sta=156.3,171.3
XS Rating Curve= 0 ,0
Exp/Cntr=0.3,0.1

Type RM Length L Ch R = 1 ,3408.6  ,396.4,388,378.6
XS GIS Cut Line= 3
     1765103.541      142181.693     1765185.631      142290.739
     1765264.998      142401.857
#Sta/Elev= 30
     9.7 1433.66    19.5 1431.88    29.2 1430.23      39 1428.69    48.7 1427.23
    58.5 1425.78    68.2  1424.4      78 1423.03    87.7 1421.68    97.5 1420.31
   107.2 1418.81     117 1417.08   126.7 1415.76     129 1415.76   136.5 1415.06
     144 1417.24   146.2 1417.68     156 1421.25   165.8    1425   175.5    1429
   185.3 1434.07     195 1440.45   204.8 1447.18   214.5 1453.97   224.3 1460.72
     234 1467.36   243.8 1473.95   253.5 1480.45   263.3 1486.96     273 1493.48
#Mann= 3 , 0 , 0
     9.7     .08       0     129    .045       0     144     .08       0
Bank Sta=129,144
XS Rating Curve= 0 ,0
Exp/Cntr=0.3,0.1

Type RM Length L Ch R = 1 ,3020.7  ,512.4,500,488.2
XS GIS Cut Line= 4
     1764753.381      142384.713     1764820.873      142472.866
     1764902.139      142525.206     1764998.556      142565.151
#Sta/Elev= 29
    10.1  1459.2    20.2 1454.29    30.3 1449.57    40.4    1445    50.5 1440.58
    60.6 1436.36    70.7 1432.39    80.7 1428.82    90.8  1425.6   100.9 1422.76
     111 1420.11   120.7 1418.11   159.4 1411.33   161.5 1411.21     169 1410.78
   176.5 1411.86   178.7 1412.18   188.4 1414.57     198 1416.69   207.7 1417.86
   217.2 1419.48   226.7 1422.27   236.1 1425.91   245.6 1429.83   255.1 1434.08
   264.6 1438.72   283.6 1448.65   302.6 1459.15     312 1464.19
#Mann= 3 , 0 , 0
       0      .1       0   161.5    .045       0   176.5      .1       0
Bank Sta=161.5,176.5
XS Rating Curve= 0 ,0
Exp/Cntr=0.3,0.1

Type RM Length L Ch R = 1 ,2520.7  ,321.9,321.1,320.3
XS GIS Cut Line= 4
      1764530.76      142910.014     1764608.238      142941.006
     1764716.708      142942.727     1764801.073      142934.119
#Sta/Elev= 24
     9.3 1462.37    18.5 1458.15    37.1 1449.82    64.9 1437.18    74.2 1432.91
    83.4 1428.44   103.2 1418.77     113  1413.2   122.9 1407.04   132.8 1402.81
   135.1 1402.72   142.6 1402.43   150.1 1403.73   162.3 1405.69   172.2 1406.72
   191.9 1408.36   210.8 1410.07   220.2 1411.41   229.6 1413.87     239 1417.63
   248.5 1422.24   257.9 1427.05   267.3 1431.72   276.7  1436.2
#Mann= 3 , 0 , 0
       0      .1       0   135.1    .045       0   150.1      .1       0
Bank Sta=135.1,150.1
XS Rating Curve= 0 ,0
Exp/Cntr=0.3,0.1

Type RM Length L Ch R = 1 ,2199.6  ,400.8,400,399.2
XS GIS Cut Line= 3
      1764562.04      143262.587     1764698.516      143260.064
     1764834.993       143257.54
#Sta/Elev= 30
     9.8 1429.85    19.5 1427.98    29.3 1425.81      39 1423.48    48.7 1421.03
    58.5 1418.27    68.3 1414.86      78 1410.68    87.7 1406.13    97.5 1402.11
   107.2 1399.13     117 1396.99   126.8 1395.38   136.5 1394.36   138.8 1394.35
   146.2 1394.32   153.8 1396.59     156 1397.25   165.8 1403.11   175.5 1408.48
   185.2 1413.19     195 1417.89   204.7 1422.17   214.5 1426.05   224.3  1430.6
     234 1436.65   243.7 1443.96   253.5 1451.46   263.3 1458.71     273 1465.78
#Mann= 3 , 0 , 0
       0      .1       0   138.8    .045       0   153.8      .1       0
Bank Sta=138.8,153.8
XS Rating Curve= 0 ,0
Exp/Cntr=0.3,0.1