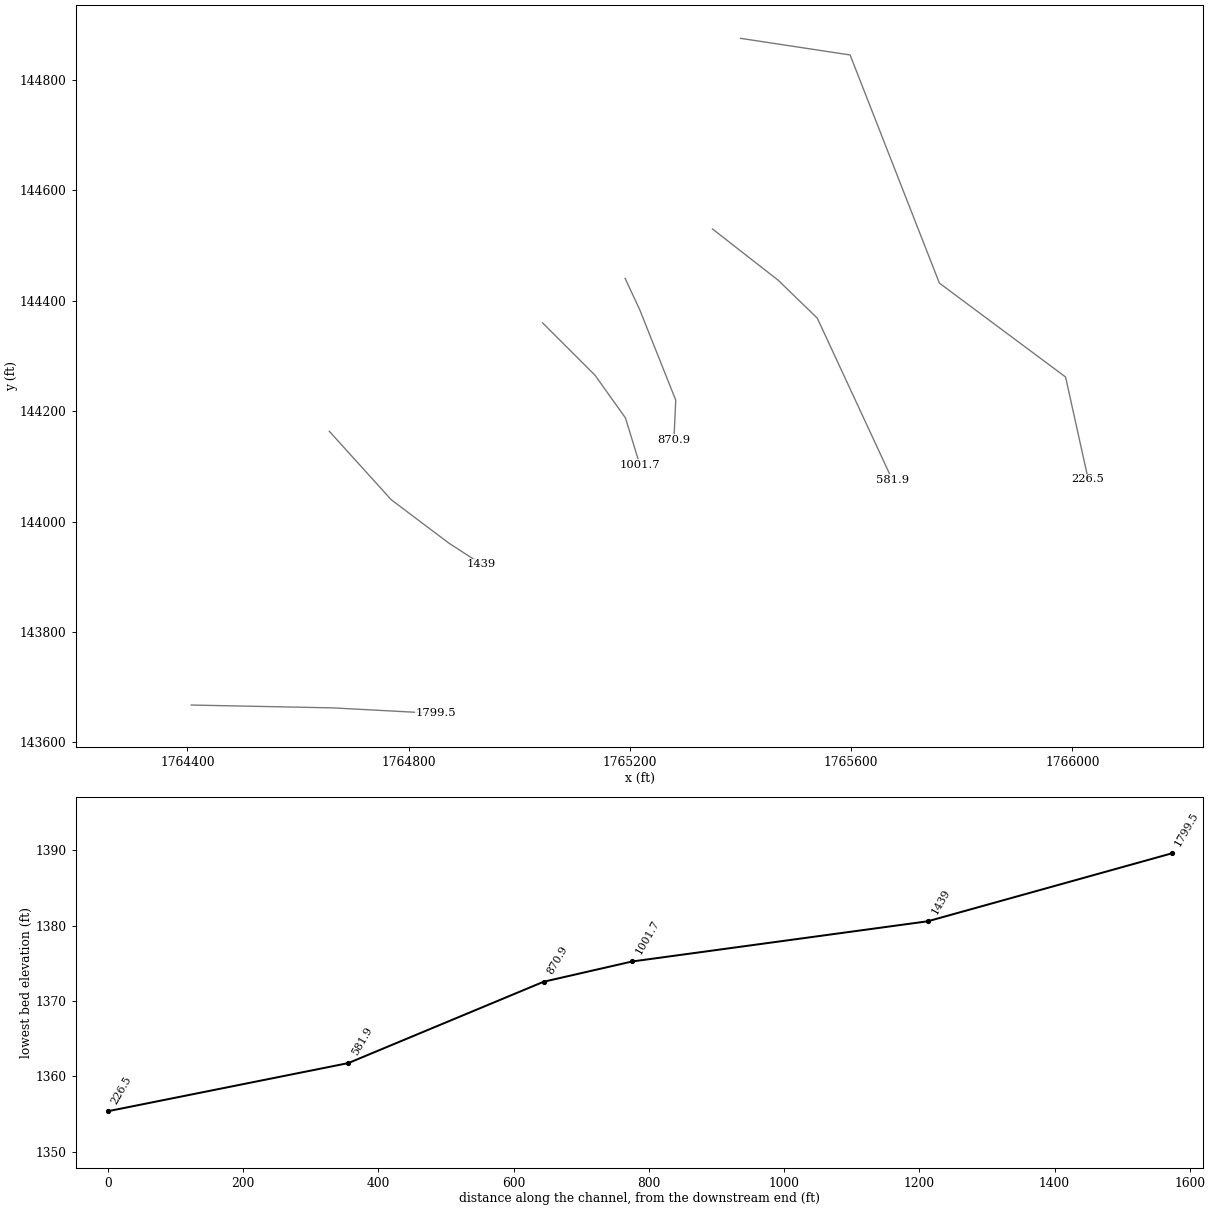
HEC-RAS study Big Branch B.prj: Big Branch B

--- Big Branch B.g01 (geometry) --- (continued)

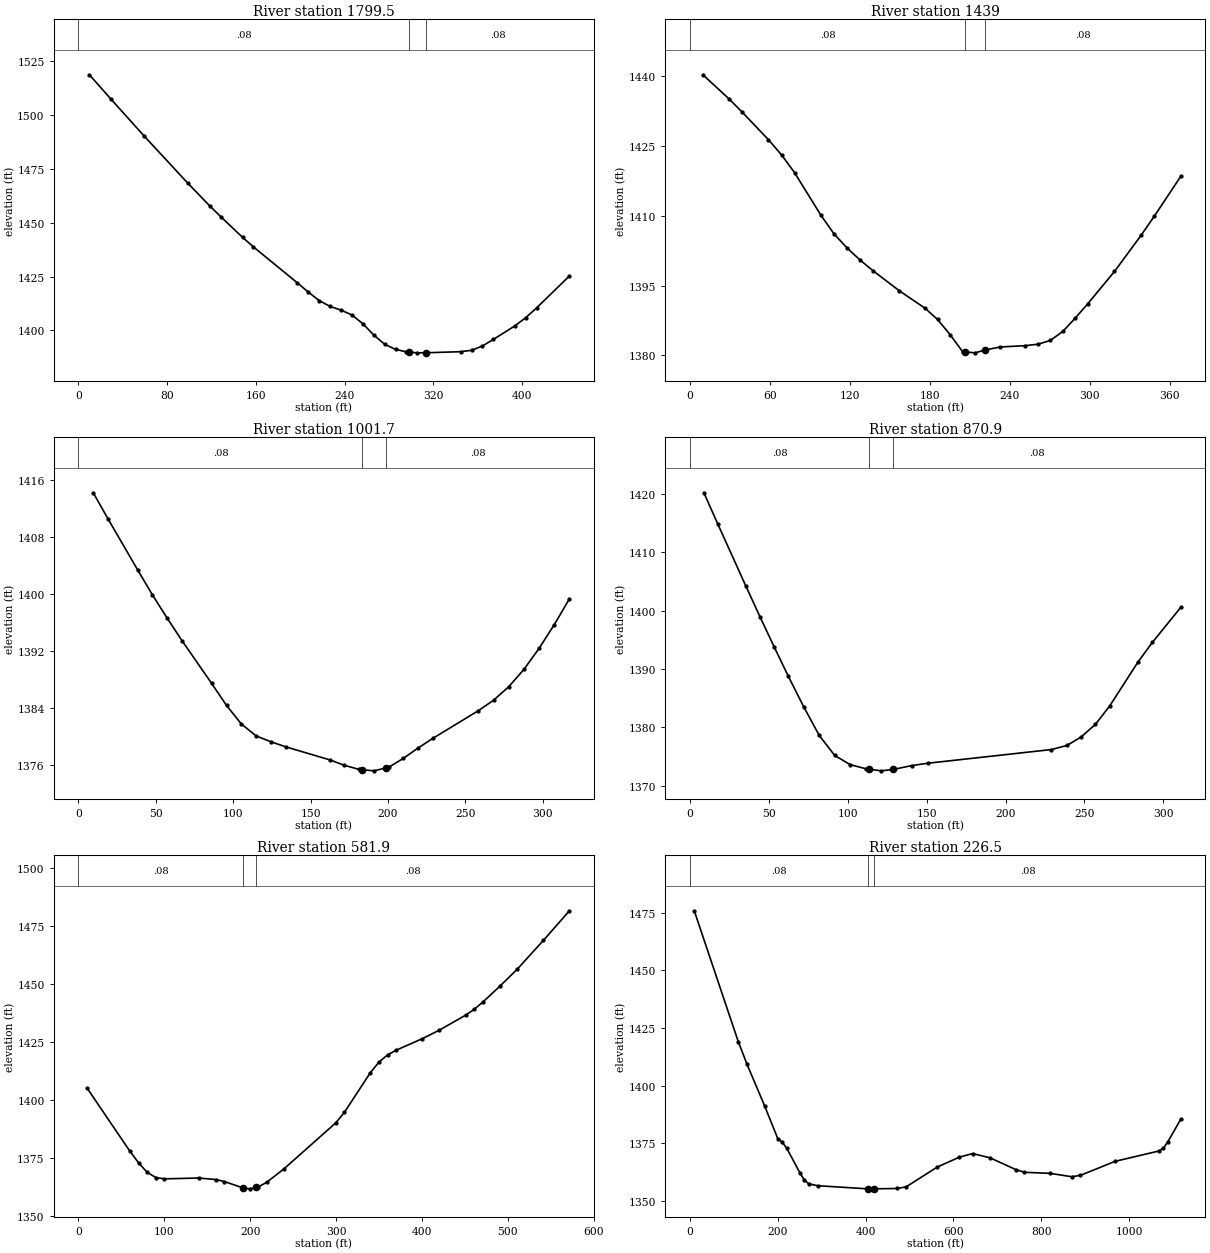
Type RM Length L Ch R = 1 ,1799.5  ,373.9,360.5,347.2
XS GIS Cut Line= 3
     1764406.795      143667.578     1764663.334      143662.413
     1764849.308      143652.474
#Sta/Elev= 30
     9.9 1518.82    29.6 1507.37    59.2  1490.4    98.7 1468.42   118.4  1457.9
   128.3  1452.9     148 1443.28   157.9 1438.79   197.4 1422.14   207.2 1417.86
   217.1  1413.9     227 1411.15   236.9 1409.43   246.7 1407.17   256.6 1403.07
   266.4 1397.84   276.2 1393.56     286 1391.17   295.8 1390.04   298.1 1389.93
   305.6 1389.58   313.1 1389.61   344.8 1390.11   354.6 1390.75   364.4 1392.78
   374.2  1395.8   393.8 1402.17   403.6    1406   413.4 1410.56   442.8  1425.3
#Mann= 3 , 0 , 0
       0     .08       0   298.1    .045       0   313.1     .08       0
Bank Sta=298.1,313.1
XS Rating Curve= 0 ,0
Exp/Cntr=0.3,0.1

Type RM Length L Ch R = 1 ,1439    ,444.8,437.3,429.8
XS GIS Cut Line= 4
     1764656.447      144163.438      1764768.36      144039.473
     1764873.386      143960.273     1764931.925      143922.395
#Sta/Elev= 30
     9.8 1440.28    29.5 1435.07    39.3 1432.24    58.9 1426.36    68.8 1423.06
    78.6 1419.24    98.2 1410.16   108.1 1406.12   117.9  1403.1   127.7 1400.49
   137.5 1398.18   157.2 1393.88   176.4 1390.15   185.8 1387.74   195.2 1384.48
   204.6 1380.81   206.5 1380.76     214 1380.57   221.5 1381.19   232.8 1381.83
   251.6 1382.11     261 1382.42   270.4 1383.23   279.8 1385.18   289.2 1388.07
   298.5 1391.12   318.5 1398.04   338.4 1405.78   348.4 1409.92   368.3  1418.5
#Mann= 3 , 0 , 0
       0     .08       0   206.5    .045       0   221.5     .08       0
Bank Sta=206.5,221.5
XS Rating Curve= 0 ,0
Exp/Cntr=0.3,0.1

Type RM Length L Ch R = 1 ,1001.7  ,135.3,130.8,126
XS GIS Cut Line= 4
     1765042.116      144359.716     1765136.811       144265.02
     1765191.907      144187.542     1765217.733      144103.177
#Sta/Elev= 29
     9.6 1414.24    19.1 1410.59    38.3 1403.41    47.8 1399.93    57.4 1396.63
      67 1393.47    86.1 1387.49    95.7  1384.4   105.2 1381.82   114.8 1380.13
   124.4 1379.31   133.9  1378.6   162.4 1376.77   171.9    1376   181.5 1375.42
   183.5 1375.38     191 1375.23   198.5 1375.63   200.5 1375.74     210 1376.99
   219.5 1378.44     229 1379.79   258.4 1383.67   268.2 1385.14     278 1387.03
   287.8 1389.46   297.6 1392.41   307.4 1395.73   317.2 1399.36
#Mann= 3 , 0 , 0
       0     .08       0   183.5    .045       0   198.5     .08       0
Bank Sta=183.5,198.5
XS Rating Curve= 0 ,0
Exp/Cntr=0.3,0.1

Type RM Length L Ch R = 1 ,870.9   ,279.4,288.9,298.7
XS GIS Cut Line= 4
     1765191.261      144440.422     1765217.551      144383.894
     1765282.792      144219.818       1765279.5      144147.727
#Sta/Elev= 24
     8.9 1420.21    17.8 1414.79    35.6 1404.15    44.5 1398.91    53.4  1393.8
    62.3  1388.8    72.2 1383.49      82  1378.6    91.8 1375.17   101.6  1373.6
   111.4 1372.91   113.7 1372.83   121.2 1372.54   128.7 1372.77   140.8 1373.45
   150.6 1373.84   229.1 1376.19   238.9 1376.89   247.9 1378.34     257 1380.52
     266 1383.66     284 1391.22     293 1394.55   311.1 1400.58
#Mann= 3 , 0 , 0
       0     .08       0   113.7    .045       0   128.7     .08       0
Bank Sta=113.7,128.7
XS Rating Curve= 0 ,0
Exp/Cntr=0.3,0.1

Type RM Length L Ch R = 1 ,581.9   ,361.7,355.5,354.8
XS GIS Cut Line= 4
     1765349.282      144529.824     1765467.651      144437.281
     1765538.673      144368.411     1765674.259      144075.716
#Sta/Elev= 30
      10 1405.15    60.1 1377.87    70.1 1372.92    80.1 1368.86    90.2  1366.6
   100.2 1366.04   140.2  1366.4   160.1 1365.74     170 1364.88   192.2 1362.08
   199.7 1361.74   207.2 1362.38   209.6 1362.58   219.5 1364.61   239.3 1370.31
   299.6  1390.1   309.7 1394.63   339.9 1411.68     350  1416.3   360.1 1419.41
   370.1 1421.42   400.4 1426.35   420.5 1430.07   450.8 1436.46   460.9    1439
     471 1442.13   491.1 1449.05   511.3 1456.38   541.5 1468.67   571.8 1481.42
#Mann= 3 , 0 , 0
       0     .08       0   192.2    .045       0   207.2     .08       0
Bank Sta=192.2,207.2
XS Rating Curve= 0 ,0
Exp/Cntr=0.3,0.1

Type RM Length L Ch R = 1 ,226.5   ,223.8,226.5,223.5
XS GIS Cut Line= 5
     1765400.022       144875.16     1765598.021       144845.03
     1765759.434      144431.813     1765987.564      144261.792
     1766028.455      144076.705
#Sta/Elev= 30
      10 1475.75   110.2 1419.11   130.2 1409.26   170.2 1391.29   200.3 1377.03
   210.4 1375.52   220.4 1372.99   250.7 1362.22   260.8 1359.19   270.9 1357.52
     291  1356.7   404.5 1355.36     412 1355.35   419.5 1355.36   472.5  1355.5
   492.7 1356.25   563.2 1364.77   613.7 1369.07   643.9 1370.63   683.1  1368.8
     742 1363.71   761.6 1362.52   820.5 1362.05   869.6 1360.59   889.2 1361.18
   968.3 1367.26  1068.1 1371.74  1078.1 1372.98    1088 1375.61    1118 1385.58
#Mann= 3 , 0 , 0
       0     .08       0   404.5    .045       0   419.5     .08       0
Bank Sta=404.5,419.5
XS Rating Curve= 0 ,0
Exp/Cntr=0.3,0.1

Chan Stop Cuts=-1
Use User Specified Reach Order=0